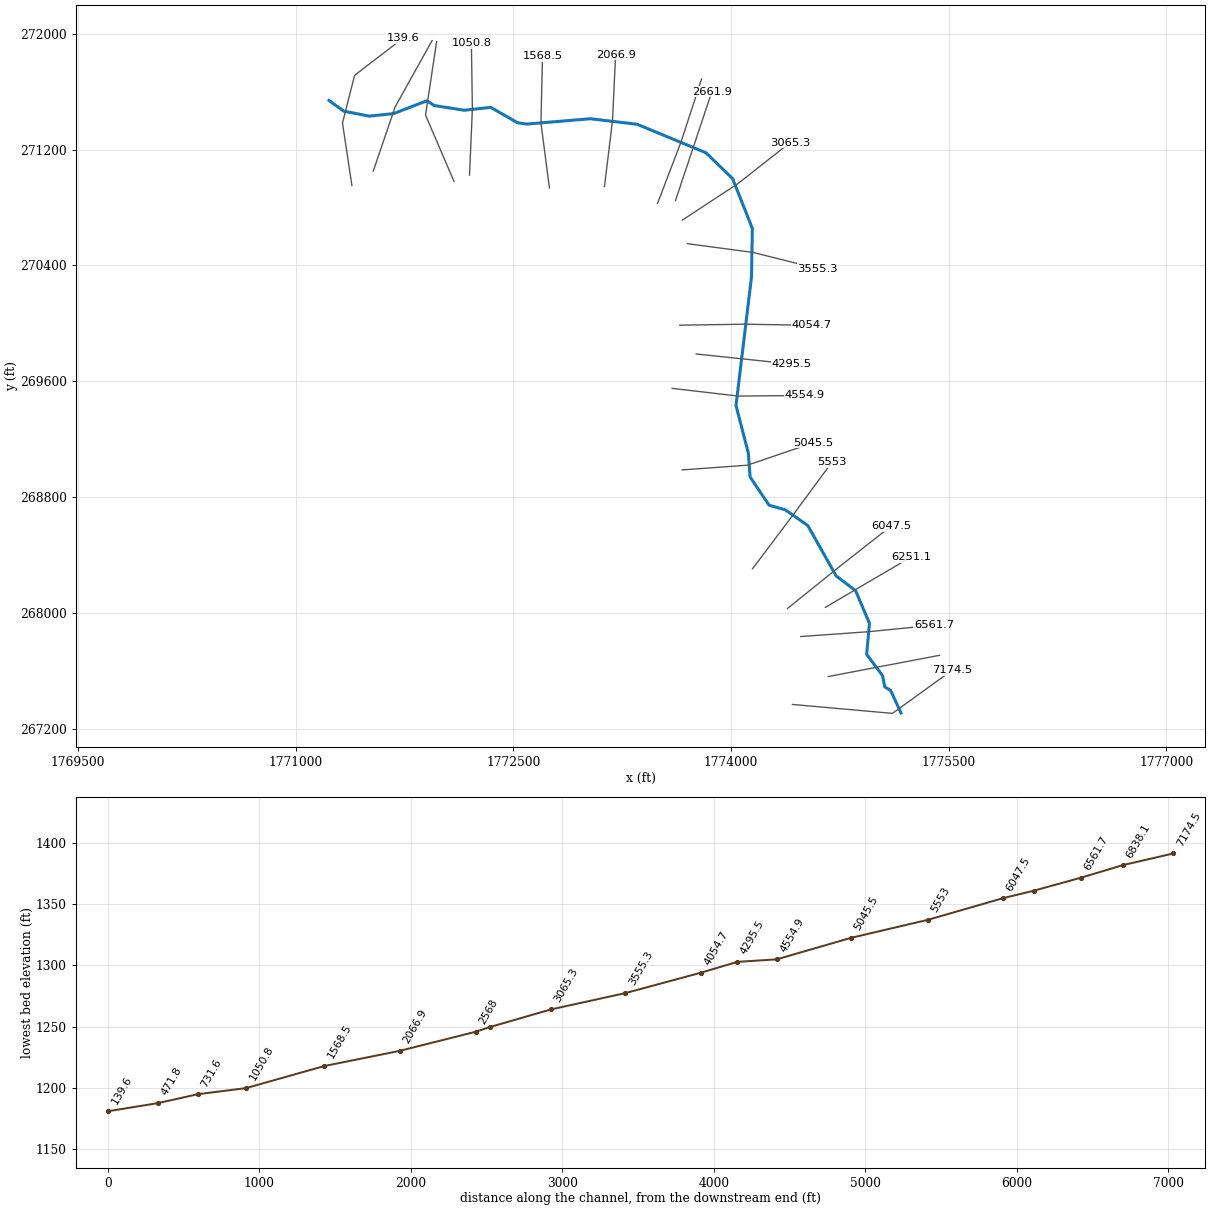
--- RoadBr.prj (project) ---

Proj Title=RoadBr
Current Plan=p01
Default Exp/Contr=0,0
English Units
Geom File=g01
Flow File=f01
Plan File=p01
BEGIN DESCRIPTION:
END DESCRIPTION:
DSS Export Rating Curves= 0
DSS Export Rating Curve Sorted= 0
DSS Export Volume Flow Curves= 0
DXF OffsetX= 0
DXF OffsetY= 0
DXF ScaleX= 0
DXF ScaleY= 0

--- RoadBr.p01 (plan) ---

Plan Title=Floodplain
Program Version=4.00
Geom File=g01
Flow File=f01
K Sum by GR=0
Std Step Tol=0.01
Critical Tol=0.01
Num of Std Step Trials=20
Max Error Tol=0.3
Flow Tol Ratio=0.001
Split Flow NTrial=30
Split Flow Tol=0.02
Split Flow Ratio=0.02
Log Output Level=0
Friction Slope Method=1
Unsteady Friction Slope Method=2
Unsteady Bridges Friction Slope Method=1
Global Log Level=0
CheckData=False
Run HTab=0
Run UNet=0
Run PostProcess=0
UNET Theta=0
UNET Theta Warmup=0
UNET ZTol=0
UNET ZSATol=0
UNET MxIter=0
UNET MaxInSteps=0
UNET DtIC=0
UNET DtMin=0
UNET MaxCRTS=0
UNET WFStab=0
UNET SFStab=0
UNET WFX=0
UNET SFX=0
UNET DSS MLevel=0
UNET DZMax Abort=0
UNET Convert EG Bridges=0
UNET Use Existing IB Tables=0
UNET Froude Limit=0
UNET Froude Power=0
Write IC File=0
Echo Input=False
Echo Output=False
Write Detailed=0

--- RoadBr.f01 (steady flow) ---

Flow Title=NFF Regression Equation
Program Version=4.00
Number of Profiles=1
Profile Names=P100yr
River Rch & RM=RoadBr,Main      ,7174.5
663.6577
River Rch & RM=RoadBr,Main      ,5553
716.5625
River Rch & RM=RoadBr,Main      ,4554.9
768.6250
River Rch & RM=RoadBr,Main      ,2661.9
816.5206
River Rch & RM=RoadBr,Main      ,2661.9
916.7687
River Rch & RM=RoadBr,Main      ,139.6
963.4112
Boundary for River Rch & Prof#=RoadBr,Main      ,1
Up Type=0
Dn Type=3
Dn Slope=0.021209

--- RoadBr.g01 (geometry) ---

Geom Title=USGS 10m DEM
Program Version=4.00

River Reach=RoadBr          ,Main
Reach XY= 30
     1775171.331      267309.171     1775100.378      267464.918
      1775059.95      267489.155     1775043.958      267567.725
     1774934.795      267714.435     1774954.264      267927.895
     1774858.513      268154.175     1774724.812      268255.385
     1774529.089      268603.876      1774373.68      268712.204
     1774262.431      268744.188     1774131.713      268938.875
     1774119.197      269105.053      1774034.55      269432.407
     1774141.447      270321.845     1774147.009      270655.593
     1774011.424      270999.076      1773826.99       271177.83
     1773353.662      271374.543     1773031.038      271412.785
     1772593.029      271375.903     1772528.145      271385.427
     1772344.072      271491.355     1772161.901      271471.191
     1771955.931       271504.08     1771902.892      271536.282
     1771673.689      271447.884     1771506.364      271430.835
     1771331.702      271464.933     1771229.532      271539.097

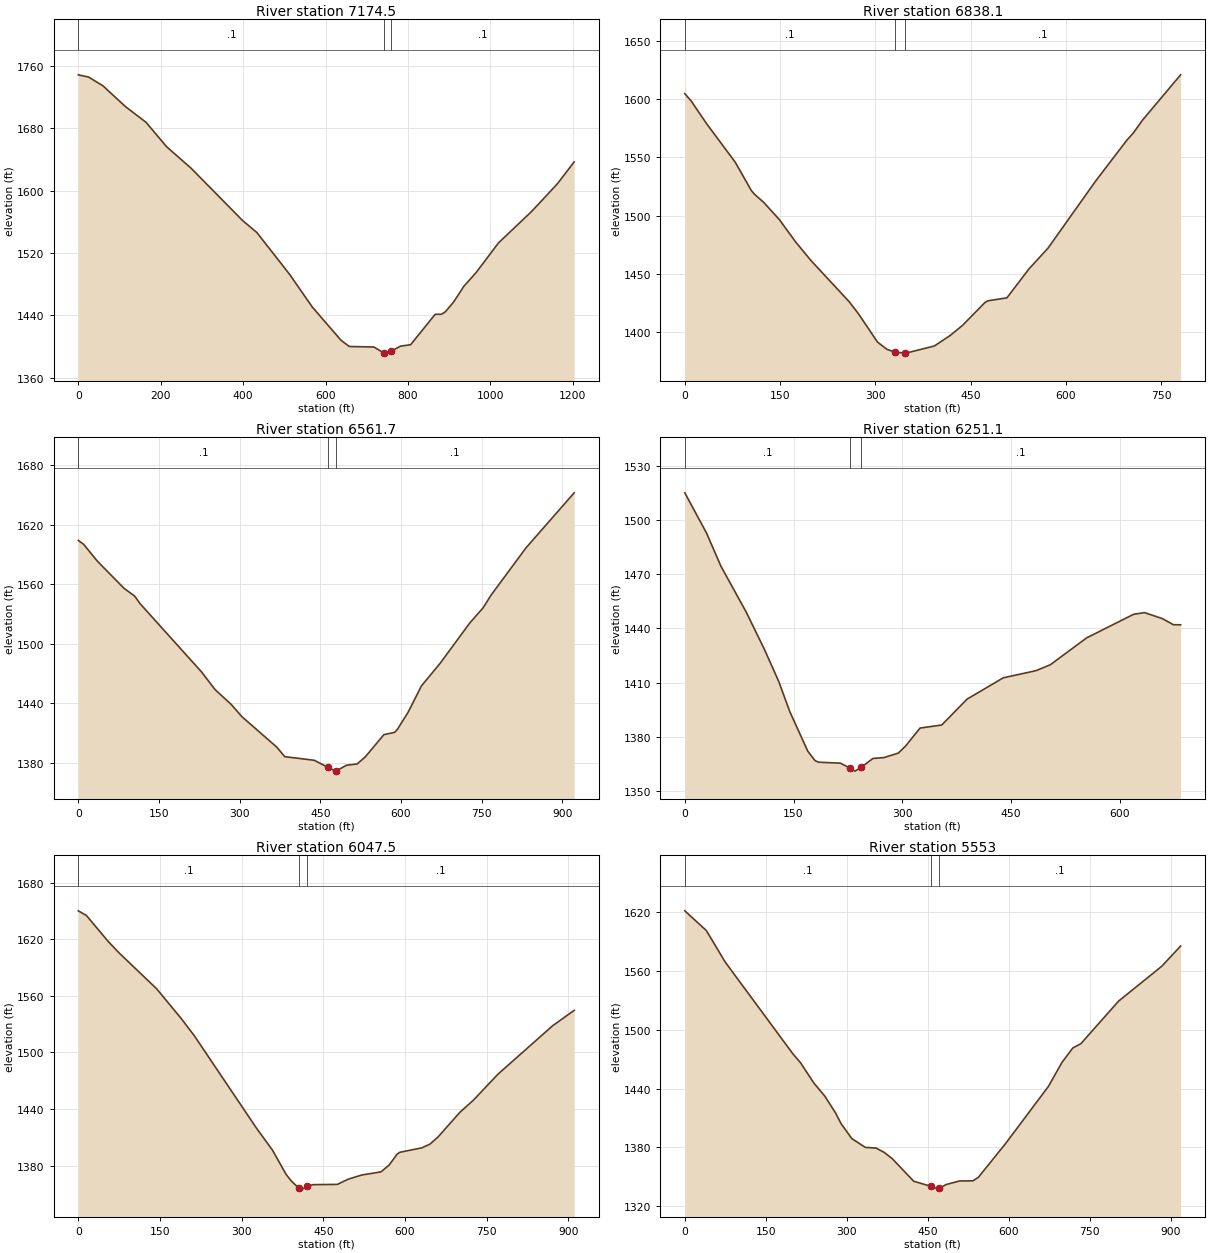
Type RM Length L Ch R = 1 ,7174.5  ,349.1,336.4,324.4
XS GIS Cut Line= 3
     1774423.062       267368.11     1775112.894      267306.449
     1775526.355      267606.442
#Sta/Elev= 30
       0 1748.28    24.9 1745.41    59.8 1734.17   114.6 1707.47   164.4  1687.4
   214.2 1656.17     274 1628.44   398.6  1561.6   433.5 1546.11   513.2  1492.3
     568 1450.63   637.8 1408.02   657.7 1400.15   717.4 1399.52   742.2 1391.66
     743  1391.7     758 1393.85   781.8 1400.53   806.6 1402.51   866.2 1441.46
     881  1441.4     891 1444.75   910.8 1457.11   935.6 1477.22   965.4  1494.9
  1019.9 1533.01  1099.3 1572.75  1138.9 1595.08  1163.7 1609.34  1203.4 1636.72
#Mann= 3 , 0 , 0
       0      .1       0     743    .045       0     758      .1       0
Bank Sta=743,758
XS Rating Curve= 0 ,0
Exp/Cntr=0.3,0.1

Type RM Length L Ch R = 1 ,6838.1  ,276.4,276.4,276.2
XS GIS Cut Line= 2
     1774669.706      267560.801     1775436.615      267707.246
#Sta/Elev= 30
       0 1604.76      10 1598.45    34.8  1578.6    79.6 1545.74   104.4  1521.9
   109.4 1518.55   124.3 1511.38   149.2 1496.44   174.1 1477.74   198.9 1461.35
   258.6 1426.28   273.5 1415.76   303.4 1391.53   318.3 1385.22   331.7 1382.76
   346.7 1382.07   348.1 1381.98   392.9 1388.09   417.7 1397.04   437.6 1405.92
   472.4 1425.28   477.4 1426.92   507.2 1429.42   542.1 1454.35   571.9 1472.04
   646.5 1529.34   696.2 1564.83   706.2 1570.86   721.1  1582.2   780.8 1620.88
#Mann= 3 , 0 , 0
       0      .1       0   331.7    .045       0   346.7      .1       0
Bank Sta=331.7,346.7
XS Rating Curve= 0 ,0
Exp/Cntr=0.3,0.1

Type RM Length L Ch R = 1 ,6561.7  ,300.6,310.6,320
XS GIS Cut Line= 3
     1774480.531      267837.096     1774947.961      267870.405
     1775399.075      267915.369
#Sta/Elev= 30
       0 1604.09      10 1600.15    34.9  1583.5    84.8 1555.95   104.7 1548.05
   114.7 1540.48   229.3 1471.52   254.2 1453.89   284.2 1438.95   304.1  1426.6
   368.9 1395.94   383.9 1386.28   438.7 1382.63   464.6 1375.42   478.6 1371.71
   479.6 1371.89   498.5  1377.6   518.4 1378.93   533.4 1385.93   568.2 1408.44
   588.2  1410.8   593.2 1413.69   613.1 1430.86     638 1457.54   672.9 1480.39
   727.7 1520.82   752.6 1536.18   767.5    1549   832.3 1596.53     922 1652.06
#Mann= 3 , 0 , 0
       0      .1       0   464.6    .045       0   479.6      .1       0
Bank Sta=464.6,479.6
XS Rating Curve= 0 ,0
Exp/Cntr=0.3,0.1

Type RM Length L Ch R = 1 ,6251.1  ,199.6,203.5,207.3
XS GIS Cut Line= 2
     1774650.437      268038.674      1775240.07      268385.517
#Sta/Elev= 30
       0 1515.03      30 1492.77    49.9 1474.42    84.9 1448.94   109.8 1428.49
   129.8 1410.54   144.8 1394.08   169.8 1372.03   179.8 1366.86   184.8 1366.02
   214.7 1365.51   228.1 1362.77   234.7  1361.1   243.1 1363.13   259.6  1368.1
   274.6 1368.58   294.6 1371.08   304.6 1374.98   324.6 1384.91   354.5 1386.62
   389.5 1400.93   439.4 1412.71   484.4 1416.65   504.3 1419.92   554.3 1434.77
   619.2 1447.84   634.2 1448.79   659.1 1445.44   674.1 1442.08   684.1 1442.04
#Mann= 3 , 0 , 0
       0      .1       0   228.1    .045       0   243.1      .1       0
Bank Sta=228.1,243.1
XS Rating Curve= 0 ,0
Exp/Cntr=0.3,0.1

Type RM Length L Ch R = 1 ,6047.5  ,489.1,494.6,500.5
XS GIS Cut Line= 3
     1774389.844      268031.096     1774744.515      268317.393
     1775101.899      268598.769
#Sta/Elev= 30
       0 1650.34    14.9 1645.37    54.5 1618.09    74.3    1606   143.7 1567.69
   188.3 1536.53     213 1517.82     327 1419.88   356.7 1396.27   381.5 1370.75
   391.4 1363.46   405.7 1355.68   411.2 1354.98   420.7 1357.95     431 1359.72
   475.8 1360.01   495.8 1365.56   520.8 1369.99   555.8 1373.27   570.8 1380.49
   585.8 1392.32   590.8  1394.1   630.8 1398.78   645.7 1402.68   660.7 1410.32
   700.7 1436.44   725.7 1449.43   770.7 1476.95   870.7 1528.14   910.7 1544.74
#Mann= 3 , 0 , 0
       0      .1       0   405.7    .045       0   420.7      .1       0
Bank Sta=405.7,420.7
XS Rating Curve= 0 ,0
Exp/Cntr=0.3,0.1

Type RM Length L Ch R = 1 ,5553    ,524.2,507.5,493.6
XS GIS Cut Line= 3
     1774148.529      268305.413     1774427.197      268676.309
     1774696.767      269042.129
#Sta/Elev= 30
       0 1621.42    39.9 1601.32    74.8 1569.14   199.5 1475.95   214.5 1466.21
   239.4 1445.33   259.4 1432.22   279.4 1414.92   289.3 1404.26   309.3 1388.93
   334.2 1379.96   354.2 1379.22   369.1 1374.87   384.1 1368.47     424 1345.34
   456.4 1340.12   468.9 1337.31   471.4  1338.1   483.9 1341.99   508.9 1345.63
   533.8 1345.81   543.8 1349.44   593.8  1383.6   673.6  1442.3   698.6 1466.73
   718.6  1481.4   733.6 1485.82   803.5  1529.3   883.4 1564.84   918.3 1585.49
#Mann= 3 , 0 , 0
       0      .1       0   456.4    .045       0   471.4      .1       0
Bank Sta=456.4,471.4
XS Rating Curve= 0 ,0
Exp/Cntr=0.3,0.1

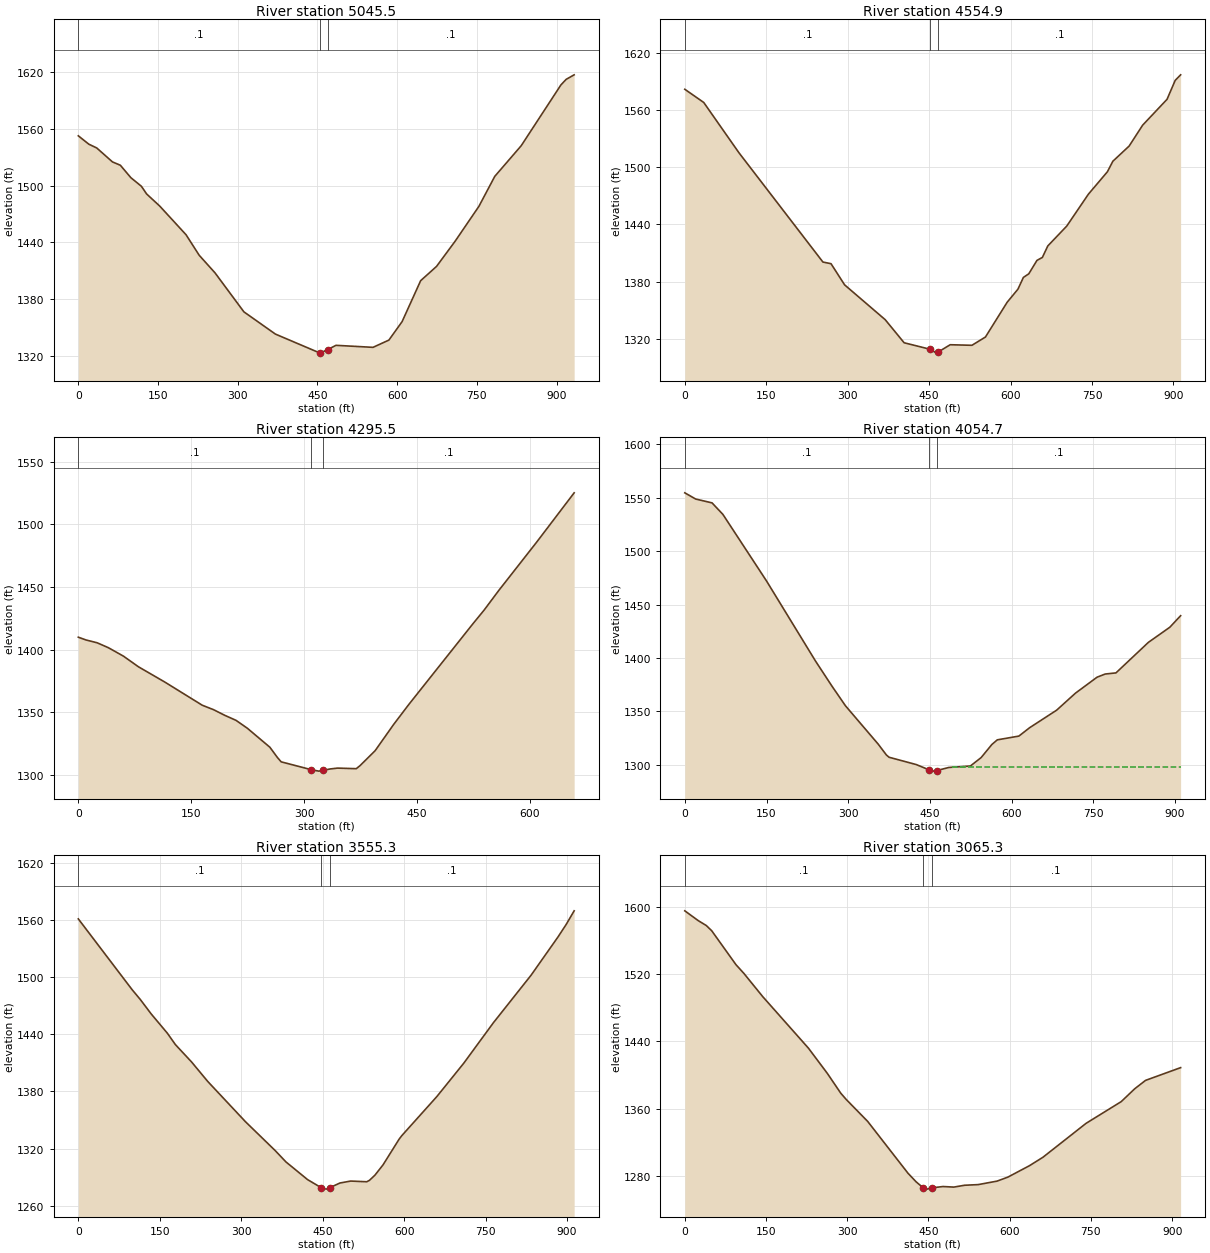
Type RM Length L Ch R = 1 ,5045.5  ,497.8,490.5,483.1
XS GIS Cut Line= 3
     1773664.001      268987.688     1774112.854      269020.214
     1774570.125      269176.253
#Sta/Elev= 30
       0 1552.82    19.8 1543.96    34.6 1539.98    64.3 1525.17    79.1 1521.66
    98.9 1508.46   118.7 1499.38   128.6 1491.19   153.3 1478.34   202.8 1447.97
   227.5 1426.25   257.2 1407.66   311.6 1366.31   370.9 1342.74   454.5 1322.72
     455 1322.56   469.5 1326.35   484.9 1330.83   554.6 1328.69   584.5 1336.36
   609.4 1355.96   644.3 1399.34   674.2 1414.46     709    1441   753.9 1478.08
   783.8 1509.87   833.6 1542.38   908.3 1606.78   918.2  1612.7   933.2 1617.47
#Mann= 3 , 0 , 0
       0      .1       0   454.5    .045       0   469.5      .1       0
Bank Sta=454.5,469.5
XS Rating Curve= 0 ,0
Exp/Cntr=0.3,0.1

Type RM Length L Ch R = 1 ,4554.9  ,259.1,259.4,256.9
XS GIS Cut Line= 3
      1773594.41      269550.809     1774050.188      269497.608
     1774504.487      269501.627
#Sta/Elev= 30
       0 1581.64    34.9 1567.79    99.8 1515.02   254.4 1400.47   269.3 1398.76
   294.3 1376.59   369.1 1340.05     404 1315.84   451.4 1309.08   463.9 1304.98
   466.4 1306.03   488.8 1313.78   528.8 1313.19   553.7 1321.85   593.7  1358.3
   613.6 1372.06   623.6 1384.35   633.6 1388.17   648.6 1402.22   658.6 1405.34
   668.6 1417.38   703.5 1438.21   743.4 1471.68   778.4 1495.17   788.4 1506.18
   818.3 1522.04   843.3 1544.02   888.2 1571.12   903.2 1590.96   913.2 1596.78
#Mann= 3 , 0 , 0
       0      .1       0   451.4    .045       0   466.4      .1       0
Bank Sta=451.4,466.4
XS Rating Curve= 0 ,0
Exp/Cntr=0.3,0.1

Type RM Length L Ch R = 1 ,4295.5  ,238.1,240.8,242.8
XS GIS Cut Line= 2
     1773760.206      269788.306     1774415.354      269718.937
#Sta/Elev= 30
       0 1409.84      10 1407.66      25 1405.38    39.9 1401.46    59.9 1394.73
    79.9 1386.21   114.8 1374.07   164.7 1355.52   179.7 1351.97   194.6 1347.47
   209.6 1343.44   224.6 1337.15   254.5    1322   264.5 1313.84   269.5 1310.35
   309.5 1304.08   319.4 1302.93   324.5 1303.48   334.4 1304.64   344.4 1305.34
   369.3 1304.88   374.3 1307.31   394.3  1319.2   419.2 1340.38   439.2  1356.2
     524 1420.34     539 1431.35     559 1447.41   608.9 1485.66   658.8 1525.08
#Mann= 3 , 0 , 0
       0      .1       0   309.5    .045       0   324.5      .1       0
Bank Sta=309.5,324.5
XS Rating Curve= 0 ,0
Exp/Cntr=0.3,0.1

Type RM Length L Ch R = 1 ,4054.7  ,502.7,499.3,494.3
XS GIS Cut Line= 3
     1773646.077      269987.142     1774100.972      269993.983
     1774556.199      269985.864
#Sta/Elev= 30
       0 1554.73      20  1548.9      50 1545.32      70  1534.5     150  1472.2
     240 1397.14     270 1373.79     295 1355.24     355 1319.38     370 1309.24
     375 1307.06     425  1300.2   447.4 1295.48     455 1294.07   462.4 1294.58
   484.6  1297.5   524.2 1298.85     544 1306.75   563.8 1319.07   573.7 1323.37
   613.3 1326.89   633.1 1334.76   682.6 1351.16   717.2 1367.11   756.8 1382.05
   771.7 1385.01   791.5 1386.07   850.9 1414.62   890.4 1428.85   910.2 1439.65
#Mann= 3 , 0 , 0
       0      .1       0   447.4    .045       0   462.4      .1       0
#XS Ineff= 2 , 0
                          490.51         1297.85
Permanent Ineff=
       F       F
Bank Sta=447.4,462.4
XS Rating Curve= 0 ,0
Exp/Cntr=0.3,0.1

Type RM Length L Ch R = 1 ,3555.3  ,473.9,490,509.3
XS GIS Cut Line= 3
     1773699.791      270550.048     1774152.676      270489.332
     1774595.288      270378.391
#Sta/Elev= 30
       0    1561    99.3 1486.55   114.2 1476.38   134.1 1461.33   163.9 1441.08
   178.8 1429.06   208.6 1410.83   238.4 1390.36   307.9 1348.09   362.6 1317.82
   382.4 1305.92   422.2 1287.36   447.7 1278.76   456.9 1277.36   462.7 1278.73
   481.7 1283.77   501.6 1285.82   531.3  1285.1   536.3 1286.64   546.2 1291.97
   561.1 1302.74   590.8 1329.79   595.8 1333.52   660.3 1374.51   709.9 1409.56
   764.4 1451.98   833.9 1501.94   883.5 1542.11   898.4 1555.09   913.2 1569.49
#Mann= 3 , 0 , 0
       0      .1       0   447.7    .045       0   462.7      .1       0
Bank Sta=447.7,462.7
XS Rating Curve= 0 ,0
Exp/Cntr=0.3,0.1

Type RM Length L Ch R = 1 ,3065.3  ,388.1,403.5,418
XS GIS Cut Line= 3
     1773664.553      270712.558     1774050.267      270966.596
     1774406.653      271247.514
#Sta/Elev= 30
       0  1595.3    24.8 1583.66    39.7 1577.79    49.7 1571.59    94.4 1531.29
   109.3 1520.68     144 1493.11   228.4 1431.78   263.2 1401.83     288 1378.25
     298 1370.84   337.7 1344.66   412.2 1282.94   427.1 1272.78   440.6 1265.39
     447 1264.04   455.6 1265.52   476.8 1267.13   496.8 1266.46   516.7 1268.65
   541.6 1269.41   576.6 1273.56   596.5  1278.3   636.4  1291.9   661.3 1301.94
   741.1 1342.39   805.9 1368.19   830.9 1383.52   850.8 1393.47   915.6 1408.64
#Mann= 3 , 0 , 0
       0      .1       0   440.6    .045       0   455.6      .1       0
Bank Sta=440.6,455.6
XS Rating Curve= 0 ,0
Exp/Cntr=0.3,0.1

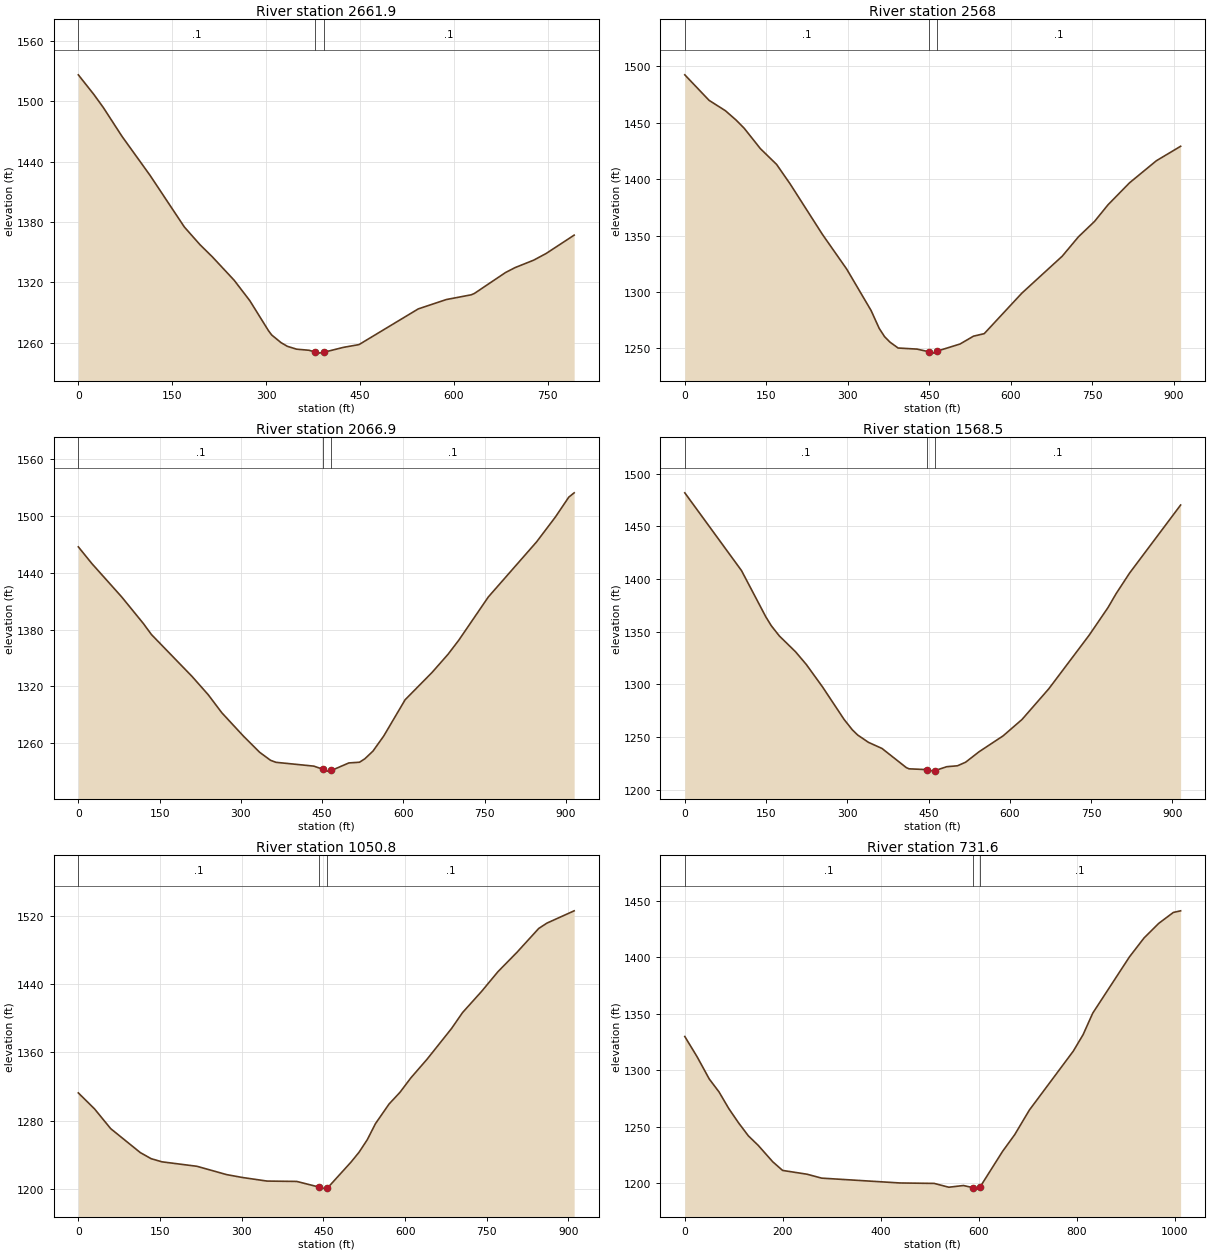
Type RM Length L Ch R = 1 ,2661.9  ,94.8,93.9,94.1
XS GIS Cut Line= 2
     1773617.615      270848.104     1773868.112      271599.598
#Sta/Elev= 30
       0 1526.38    24.9 1506.78    39.9 1493.88    69.8 1465.16   114.6 1426.38
   169.4 1375.03   194.3  1357.5   214.2 1345.31   249.1 1321.99     274 1301.74
   303.9 1271.81   308.9 1267.67   323.8 1260.08   333.8 1256.42   348.7 1253.55
   368.7 1252.46   377.7 1250.75   383.6 1249.62   392.7 1250.55   423.5 1255.35
   448.4  1258.1     543 1293.58   587.9 1302.91   627.7 1307.62   632.7 1308.96
   682.5 1329.78   697.5 1334.61   727.4 1342.06   747.3 1348.69   792.1 1366.96
#Mann= 3 , 0 , 0
       0      .1       0   377.7    .045       0   392.7      .1       0
Bank Sta=377.7,392.7
XS Rating Curve= 0 ,0
Exp/Cntr=0.3,0.1

Type RM Length L Ch R = 1 ,2568    ,495.5,501,507.1
XS GIS Cut Line= 3
      1773493.63      270827.723     1773656.509      271254.628
     1773797.046      271687.622
#Sta/Elev= 30
       0  1492.6    44.7 1469.95    74.5 1460.85    94.4 1452.47   109.3  1445.2
   139.1 1427.11   168.9 1413.13   193.7 1395.91   253.3    1351     298  1320.2
   342.7 1283.59   357.6 1267.76   367.5 1260.39   377.5 1255.51   392.4  1250.3
   427.1 1249.33   449.4 1246.93   456.9 1245.76   464.4 1247.56   506.4 1253.85
   531.1 1260.79   550.9 1263.04   620.2    1299   694.4 1331.74   724.1 1348.87
   753.8 1362.57   778.6 1377.32   818.1 1396.77   867.6  1416.4   912.2 1429.23
#Mann= 3 , 0 , 0
       0      .1       0   449.4    .045       0   464.4      .1       0
Bank Sta=449.4,464.4
XS Rating Curve= 0 ,0
Exp/Cntr=0.3,0.1

Type RM Length L Ch R = 1 ,2066.9  ,492.8,498.4,498.9
XS GIS Cut Line= 3
     1773128.134      270944.808     1773183.548      271401.165
     1773204.812      271856.218
#Sta/Elev= 30
       0 1467.52      25 1449.83      80 1414.56   119.9  1386.5   134.9 1374.76
   209.9 1330.39   239.8 1311.01   264.8 1291.99   304.8  1267.2   334.8 1250.04
   354.8 1241.62   364.8 1239.48   434.7 1235.44   452.2 1232.01   459.7 1230.15
   467.2 1230.83   499.3 1238.81   519.1 1239.58     529 1243.24   543.9 1251.35
   563.7 1267.24   603.3 1305.71   652.8 1334.48   682.5 1353.84   702.3  1368.7
   756.8 1414.45   845.9 1472.76   880.6 1499.06   905.4 1520.15   915.3 1524.71
#Mann= 3 , 0 , 0
       0      .1       0   452.2    .045       0   467.2      .1       0
Bank Sta=452.2,467.2
XS Rating Curve= 0 ,0
Exp/Cntr=0.3,0.1

Type RM Length L Ch R = 1 ,1568.5  ,519.5,517.7,518
XS GIS Cut Line= 3
     1772748.727      270934.502     1772690.108      271384.546
     1772701.135      271845.956
#Sta/Elev= 30
       0 1481.97   104.7 1408.12   149.6 1364.21   159.6 1355.84   174.6 1346.04
   204.5 1331.03   224.4 1318.94   254.4 1297.58   294.2 1266.73   309.2    1257
   319.2 1251.98   339.1 1245.03   364.1 1239.23     409 1221.04     414  1219.9
   446.3 1219.16   458.8 1217.71   461.3 1218.11   483.6  1221.9   503.5 1222.79
   518.4 1226.16   543.2 1236.07   587.8 1251.24   622.6 1266.76   672.2    1296
   746.6 1346.82   781.4 1373.06   796.3 1386.22   821.1 1405.72   915.4 1470.38
#Mann= 3 , 0 , 0
       0      .1       0   446.3    .045       0   461.3      .1       0
Bank Sta=446.3,461.3
XS Rating Curve= 0 ,0
Exp/Cntr=0.3,0.1

Type RM Length L Ch R = 1 ,1050.8  ,321.2,319.2,316.3
XS GIS Cut Line= 3
     1772197.949      271023.743     1772217.751      271478.905
     1772210.961      271933.749
#Sta/Elev= 30
       0 1312.32    29.7 1293.64    59.4 1270.48   113.9 1242.37   133.7 1235.29
   153.5 1231.61   217.9 1226.36   272.4 1216.61   302.1 1213.18   346.6 1209.06
   401.1 1208.64   441.8 1202.07   455.6 1199.63   456.8 1200.42   500.6 1231.17
   515.6 1242.92   530.6  1257.5   545.6 1276.27   570.6 1299.29   590.6 1312.98
   610.6 1329.89   640.6 1351.94   685.5 1387.87   705.5 1406.36   740.5 1431.18
   770.5 1454.24   805.5 1476.98   845.5 1504.94   860.5 1511.17   910.5 1525.56
#Mann= 3 , 0 , 0
       0      .1       0   441.8    .045       0   456.8      .1       0
Bank Sta=441.8,456.8
XS Rating Curve= 0 ,0
Exp/Cntr=0.3,0.1

Type RM Length L Ch R = 1 ,731.6   ,265.1,259.8,254
XS GIS Cut Line= 3
     1772091.504      270979.134      1771894.96      271437.738
     1771971.404      271945.009
#Sta/Elev= 30
       0 1329.68      25 1311.85    49.9 1292.12    69.8 1280.67    89.8 1265.91
   109.8 1253.24   129.7 1241.79   149.7 1233.42   179.6 1218.78   199.6 1211.18
   249.5 1207.82   279.4 1204.35   439.1 1200.08   508.9 1199.69   538.8 1196.32
   568.7 1197.82   587.2 1196.02   598.6 1194.63   602.2 1196.25   648.4 1227.95
   673.3 1242.83   703.2 1264.59   792.8 1316.72   812.7 1331.18   832.6 1350.39
   907.4  1400.1   937.2 1416.86   967.1 1429.75     997 1439.46  1011.9  1440.9
#Mann= 3 , 0 , 0
       0      .1       0   587.2    .045       0   602.2      .1       0
Bank Sta=587.2,602.2
XS Rating Curve= 0 ,0
Exp/Cntr=0.3,0.1

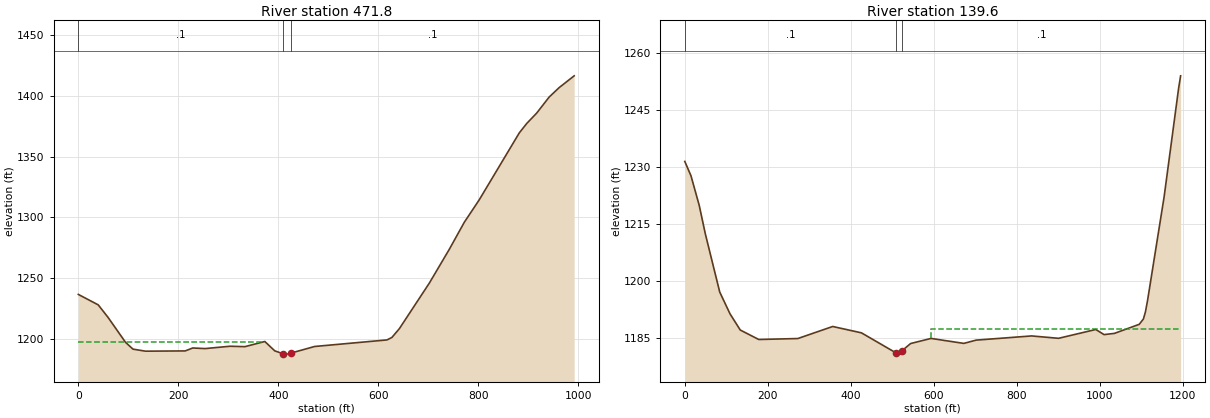
Type RM Length L Ch R = 1 ,471.8   ,329.1,332.2,335.9
XS GIS Cut Line= 3
     1771534.736      271051.813     1771685.559      271494.489
     1771940.305      271952.727
#Sta/Elev= 30
       0 1236.56    39.8 1227.96    59.7 1217.52    94.5 1197.08   109.4 1191.51
   134.3 1189.83   213.9 1190.04   228.9 1192.46   253.7 1191.96   303.5  1193.9
   333.3 1193.55   373.1  1197.8     393  1190.1   409.9 1187.65   417.9  1187.4
   424.9 1188.19   472.7 1193.69   617.5 1199.09   627.4 1201.14   642.4 1208.43
   702.4 1245.95   742.3 1273.75   772.2 1295.93   802.2 1314.49   882.1 1369.42
   897.1 1377.26     917 1385.79     942 1399.02     962 1406.78     992 1416.49
#Mann= 3 , 0 , 0
       0      .1       0   409.9    .045       0   424.9      .1       0
#XS Ineff= 2 , 0
          372.21 1197.76
Permanent Ineff=
       F       F
Bank Sta=409.9,424.9
XS Rating Curve= 0 ,0
Exp/Cntr=0.3,0.1

Type RM Length L Ch R = 1 ,139.6   ,146,139.6,133.2
XS GIS Cut Line= 4
     1771387.492      270951.856     1771322.623      271382.799
     1771406.223      271712.788     1771738.692      271967.993
#Sta/Elev= 30
       0 1231.53    14.9 1227.75    34.7 1219.98    49.5 1212.43    84.2 1197.09
     109 1191.34   133.7 1187.07   178.3 1184.57   272.4 1184.82   356.6    1188
   425.9 1186.32   508.8 1181.06   514.7 1180.71   523.8 1181.62   544.3  1183.5
   593.7 1184.85   672.6 1183.54   702.2  1184.4   836.1 1185.51     901 1184.88
   990.8 1187.21  1010.7 1185.86  1035.7 1186.18  1095.5 1188.57  1105.5 1189.96
  1110.5 1191.86  1115.5  1194.8  1155.4 1222.11  1190.4 1250.78  1195.3 1254.11
#Mann= 3 , 0 , 0
       0      .1       0   508.8    .045       0   523.8      .1       0
#XS Ineff= 2 , 0
           356.8 1187.98  593.69         1187.26
Permanent Ineff=
       F       F
Bank Sta=508.8,523.8
XS Rating Curve= 0 ,0
Exp/Cntr=0.3,0.1

Chan Stop Cuts=-1
Use User Specified Reach Order=0